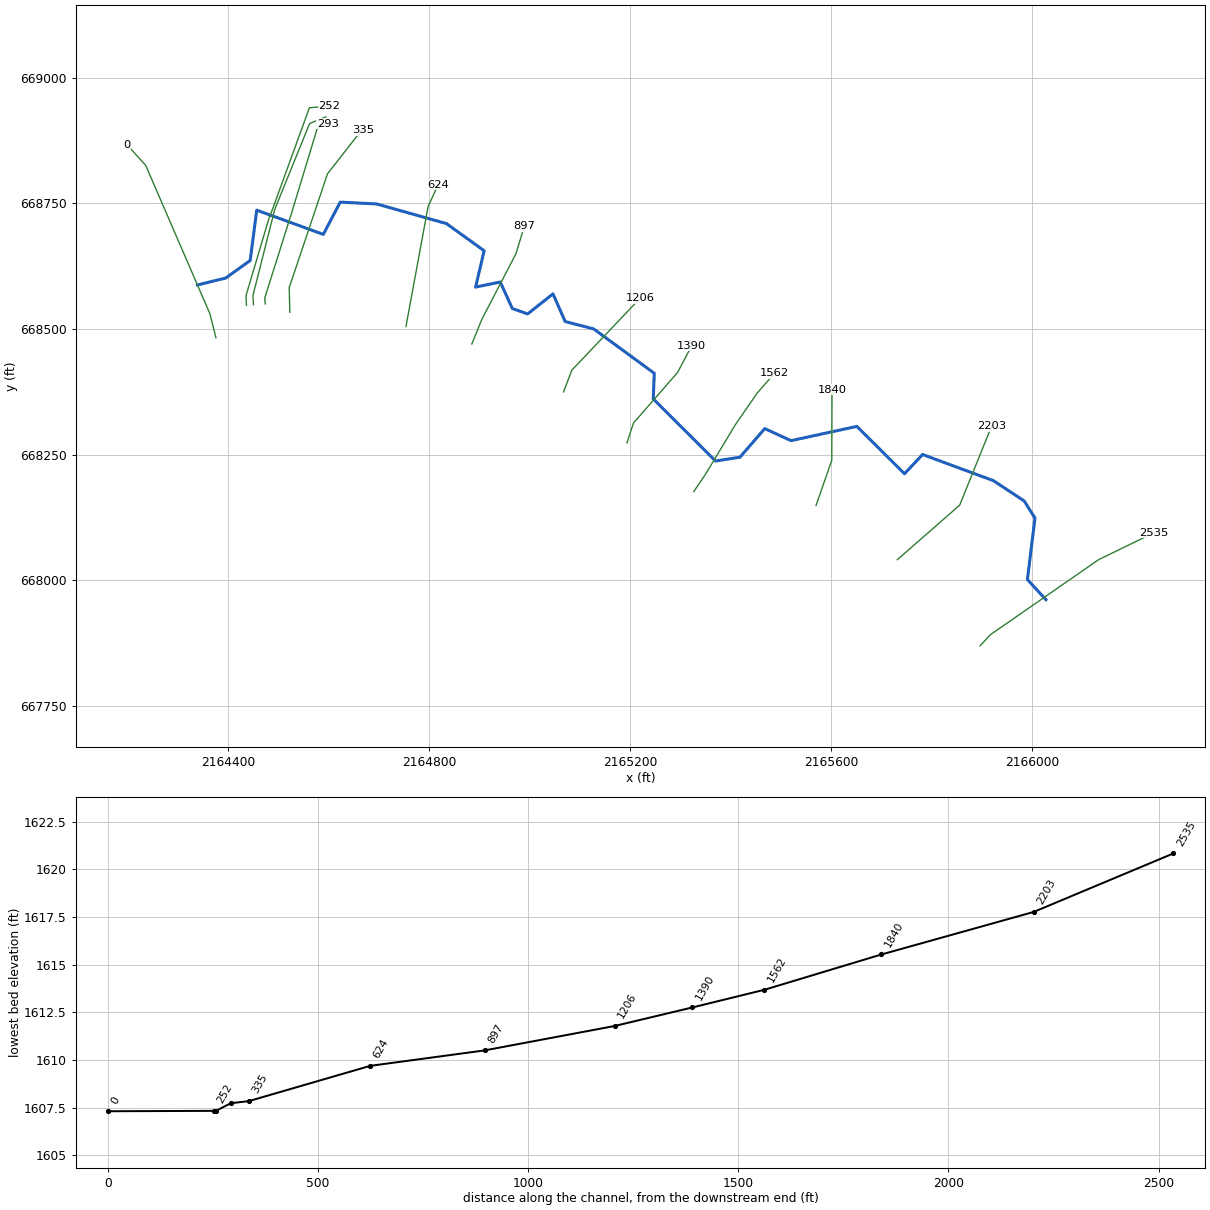
--- KANAWHRNT1.prj (project) ---

Proj Title=KANAWHRNT1
Current Plan=p01
Default Exp/Contr=0,0
English Units
Geom File=g01
Flow File=f01
Plan File=p01
BEGIN DESCRIPTION:
---------- MODELED AS PART OF WVEMD CTP PROGRAM, 2023----------
Stream Name: Kanawha Run Tributary 1
Flood Zone:  AFH
Upshur County, WV
HEC-RAS Version: RAS 6.3
Vertical Datum: NAVD88
Projection: NAD 1983 StatePlane West Virginia S FIPS 4702 (US Feet)
Terrain: 1-meter LIDAR (FEMA Region III 3DEP collected 2016-2018)
Land Use: 2019 NLCD
Hydrologic Method:
WV SIR2010-5033 regression equations
Additional Model Notes:
KWSE tie-in with Kanawha Run
END DESCRIPTION:
DSS Export Rating Curves= 0
DSS Export Rating Curve Sorted= 0
DSS Export Volume Flow Curves= 0
DXF OffsetX= 0
DXF OffsetY= 0
DXF ScaleX= 0
DXF ScaleY= 0

--- KANAWHRNT1.p01 (plan) ---

Plan Title=Floodplain
Program Version=6.30
Short Identifier=Floodplain
Geom File=g01
Flow File=f01
Subcritical Flow
K Sum by GR= 0
Std Step Tol= 0.01
Critical Tol= 0.01
Num of Std Step Trials= 20
Max Error Tol= 0.3
Flow Tol Ratio= 0.001
Split Flow NTrial= 30
Split Flow Tol= 0.02
Split Flow Ratio= 0.02
Log Output Level= 0
Friction Slope Method= 1
Unsteady Friction Slope Method= 2
Unsteady Bridges Friction Slope Method= 1
Parabolic Critical Depth
Global Vel Dist= 0 , 0 , 0
Global Log Level= 0
CheckData=False
Encroach Param=-1 ,0,0, 0
Mapping Interval=1HOUR
Computation Time Step Use Courant=        0
Computation Time Step Use Time Series=    0
Computation Time Step Count To Double=0
Computation Time Step Max Doubling=0
Computation Time Step Max Halving=0
Computation Time Step Residence Courant=0
Run HTab= 0
Run UNet= 0
Run Sediment= 0
Run PostProcess= 0
Run WQNet= 0
Run RASMapper=-1
UNET Theta= 0
UNET Theta Warmup= 0
UNET ZTol= 0
UNET ZSATol= 0
UNET MxIter= 0
UNET Max Iter WO Improvement= 0
UNET MaxInSteps= 0
UNET DtIC= 0
UNET DtMin= 0
UNET MaxCRTS= 0
UNET WFStab= 0
UNET SFStab= 0
UNET WFX= 1
UNET SFX= 1
UNET Gravity=32.17405
UNET 1D Methodology=Finite Difference
UNET DSS MLevel= 1
UNET Pardiso=0
UNET DZMax Abort= 0
UNET Use Existing IB Tables= 0
UNET Froude Reduction=False
UNET Froude Limit= 0
UNET Froude Power= 0
UNET D1 Cores= 0
UNET WindReference=Eulerian
UNET WindDragFormulation=Hsu (1988)
UNET D2 Coriolis=0
UNET D2 Cores= 0
UNET D2 Theta= 1
UNET D2 Theta Warmup= 1
UNET D2 Z Tol= 0.01
UNET D2 Volume Tol= 0.01
UNET D2 Max Iterations= 20
UNET D2 Equation= 0
UNET D2 RampUpFraction=0.1
UNET D2 TimeSlices= 1
UNET D2 Turbulence Formulation=Non-Conservative (original)
UNET D2 Eddy Viscosity=0.3
UNET D2 Transverse Eddy Viscosity=0.1
UNET D2 Smagorinsky Mixing=0
UNET D2 BCVolumeCheck=0
UNET D2 Cores=0
UNET D2 SolverType=PARDISO (Direct)
UNET D2 Minimum Iterations= 3
UNET D2 Maximum Iterations= 30
UNET D2 Restart Number= 10
UNET D2 Relaxation Coeff=1.3
UNET D2 SOR Precondition Iterations= 10
UNET D2 ILUT Maximum Fill= 8
UNET D2 ILUT Tolerance=1E-08
UNET D2 Convergence Tolerance=0.00001
UNET D1D2 MaxIter= 0
UNET D1D2 ZTol=0.01
UNET D1D2 QTol=0.1
UNET D1D2 MinQTol=1
Write IC File= 0
Write IC File at Fixed DateTime=0
Write IC File at Sim End=0
Echo Input=False
Echo Parameters=False
Echo Output=False
Write Detailed= 0
HDF Write Warmup=0
HDF Write Time Slices=0
HDF Flush=0
HDF Compression= 1
HDF Chunk Size= 1
HDF Spatial Parts= 1
HDF Use Max Rows=0
HDF Fixed Rows= 1
Calibration Method= 0
Calibration Iterations= 20
Calibration Max Change=0.05
Calibration Tolerance=0.2
Calibration Maximum=1.5
Calibration Minimum=0.5
Calibration Optimization Method= 1
WQ AD Non Conservative
WQ ULTIMATE=-1
WQ Max Comp Step=1HOUR
WQ Output Interval=15MIN
WQ Output Selected Increments= 0
WQ Output face flow=0
WQ Output face velocity=0
WQ Output face area=0
WQ Output face dispersion=0
WQ Output cell volume=0
WQ Output cell surface area=0
WQ Output cell continuity=0
WQ Output cumulative cell continuity=0
WQ Output face conc=0
WQ Output face dconc_dx=0
WQ Output face courant=0
WQ Output face peclet=0
WQ Output face adv mass=0
WQ Output face disp mass=0
WQ Output cell mass=0
WQ Output cell source sink temp=0
WQ Output nsm pathways=0
WQ Output nsm derived pathways=0
WQ Create Restart=0
WQ Fixed Restart=0
WQ System Summary=0
WQ Write To DSS=0
Sorting and Armoring Iterations= 10
XS Update Threshold= 0.02
Bed Roughness Predictor= 0
Hydraulics Update Threshold= 0.02
Energy Slope Method= 1
Volume Change Method= 1
Sediment Retention Method= 0
Sediment TS Multiplier= 1
Warm Up Method= 0
XS Weighting Method= 0
Number of US Weighted Cross Sections= 1
Number of DS Weighted Cross Sections= 1
Upstream XS Weight=0
Main XS Weight=1
Downstream XS Weight=0
Number of DS XS's Weighted with US Boundary= 1
Upstream Boundary Weight= 1
Weight of XSs Associated with US Boundary= 0
Number of US XS's Weighted with DS Boundary= 1
Downstream Boundary Weight= 0.5
Weight of XSs Associated with DS Boundary= 0.5
Percentile Method= 0
Sediment Output Level= 3
Mass or Volume Output= 0
Output Increment Type= 1
Profile and TS Output Increment= 1
Transport Output Increment 1
XS Output Flag= 0
XS Output Increment= 10
Read HDF5 Sediment Hotstart= 0
Sediment Hotstart Type= 0
Write Gradation File= 0
Read Gradation Hotstart= 0
Write HDF5 File= 1
Write Binary Output= 1
Write DSS Sediment File= 0
DSS Sediment Output Type= 1
SV Curve= 0
Specific Gage Flag= 0
Subcell Erosion Methods= 0
Subcell Deposition Methods= 0
Advection Scheme= 1
Matrix Solver= 0
Implicit Weighting Factor= 1
Maximum Outer Loop Convergence Iterations= 5
Convergence Maximum Absolute= 0.001
Convergence RMSE= 0.0001
Grain Fractions Max Abs Error= 0.001
Max Subgrid Regions= 1
Max Subgrid Length Scale= 3.402823E+38
Initial Layer Thickness= 3.402823E+38
Min Layer Thickness= 3.402823E+38
Max Layer Thickness= 3.402823E+38
Number of Layers= 5

--- KANAWHRNT1.f01 (steady flow) ---

Flow Title=Flows
Program Version=6.30
Number of Profiles= 1
Profile Names=01pct
River Rch & RM=KANAWHRNT1,Main,2535
     591
River Rch & RM=KANAWHRNT1,Main,0
    1220
Boundary for River Rch & Prof#=KANAWHRNT1,Main            , 1
Up Type= 0
Dn Type= 1
Dn Known WS=1613
DSS Import GetInterval= 0
DSS Import GetPeak= 0
DSS Import FillOption= 0

--- KANAWHRNT1.g01 (geometry) ---

Geom Title=Geometry
Program Version=6.30

River Reach=KANAWHRNT1      ,Main
Reach XY= 30
2166027.26571983667961.8116013112165990.43059887668001.947533533
      2166005.47668124.0290000142165984.15099999 668158.05399999
2165922.91200002668198.5170000342165781.94699998668250.570000023
2165746.06200001668212.3390000162165651.19900005668306.487000018
2165520.27900003668278.0989999922165468.11100003668302.137000009
     2165418.662668245.1900000272165370.10000002668237.664000019
2165246.30599998668361.1439999942165248.25200002668412.224000007
2165127.74800003668500.3340000062165071.08800003668515.072000012
2165046.85000004668570.0719999672164996.42700003668530.124000013
2164965.95100002668540.9409999852164942.05600002 668593.65200001
2164892.92200001      668583.5222164909.97700003668655.807000026
2164834.91700003 668709.863000022164696.09799999668748.895999998
2164623.72800002668752.5020000192164589.98899998668688.314999998
2164457.65887791 668736.58401899     2164444.618668636.376000017
2164395.76900001668601.436000004 2164339.7521885668587.728646412

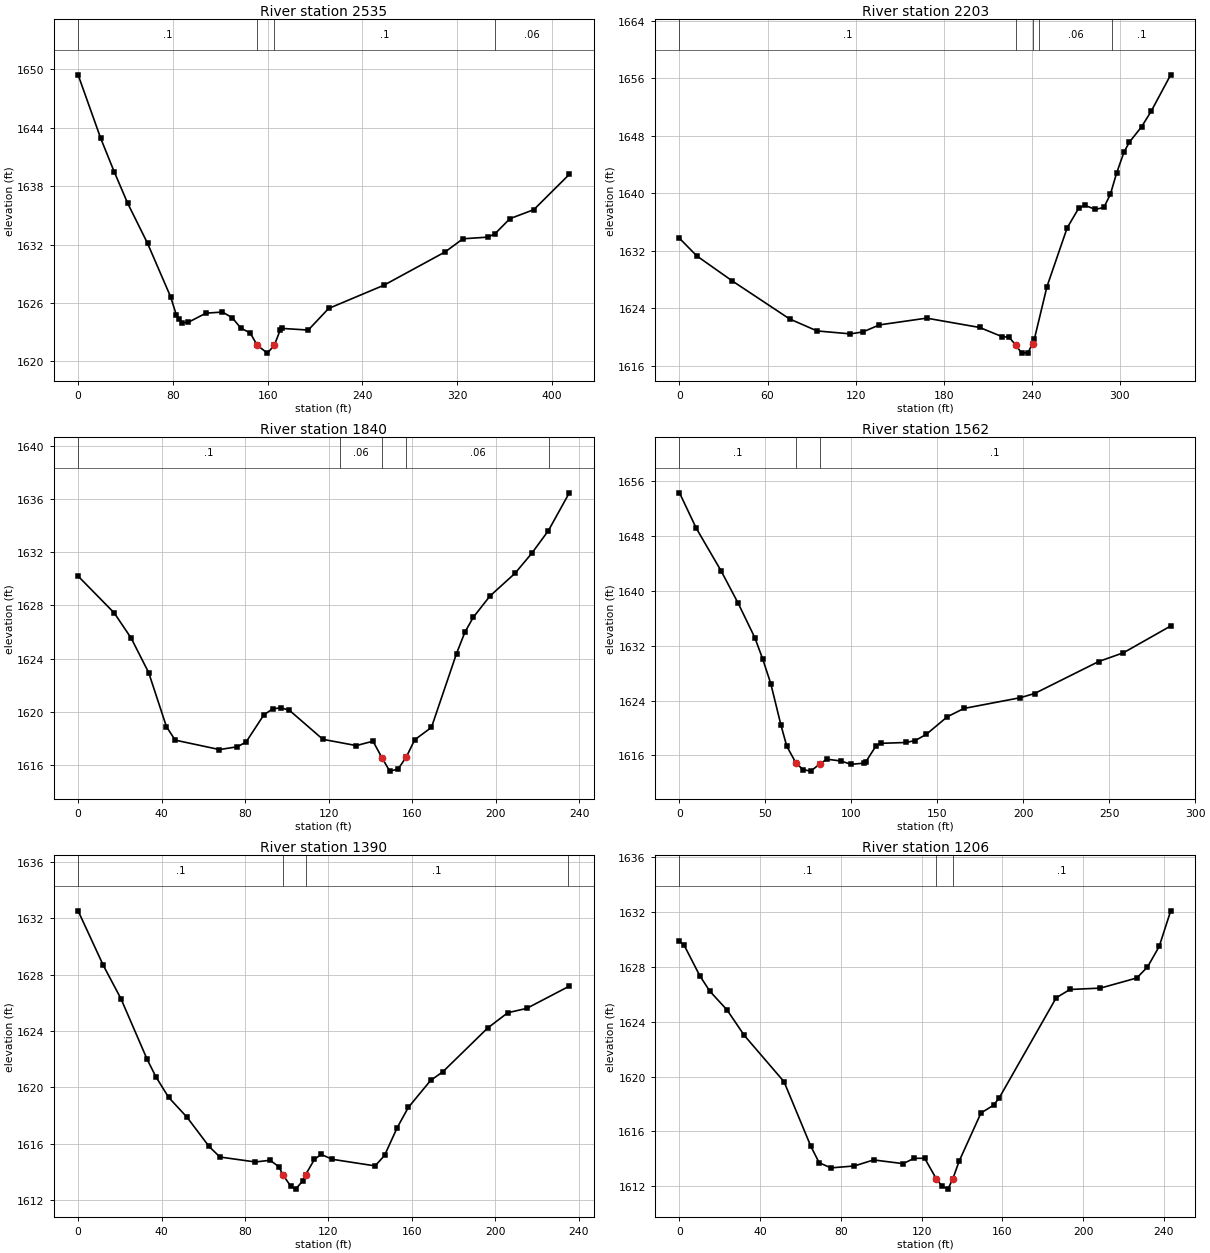
Type RM Length L Ch R = 1 ,2535    ,319.1,332.6,319.1
XS GIS Cut Line= 4
2165896.24095022667870.1312769482165917.02119621667892.344643351
2166131.98925818668041.3891663132166242.33952999668095.131181804
#Sta/Elev= 30
       0 1649.44    19.1 1642.91    30.4  1639.5    41.9 1636.23    58.6 1632.13
    78.1 1626.63    82.9 1624.78      85 1624.35    87.8 1623.97    92.7 1623.99
     108 1624.95   121.9 1625.06   130.2 1624.47   137.2 1623.44   145.4 1622.89
   151.2 1621.65   159.8 1620.84   165.7 1621.66   170.5 1623.17   172.3 1623.38
   194.3 1623.21   211.5 1625.43   258.2 1627.82     310 1631.25   324.9 1632.59
   345.8 1632.76   351.8 1633.09   364.6 1634.66   384.7 1635.58   414.7 1639.21
#Mann= 4 ,-1,0
       0      .1       0   151.2    .045       0   165.7      .1       0
     352     .06       0
Bank Sta=151.2,165.7
XS Rating Curve= 0 ,0
Exp/Cntr(USF)=0,0
Exp/Cntr=0.3,0.1

Type RM Length L Ch R = 1 ,2203    ,353,362.2,362.7
XS GIS Cut Line= 3
2165731.72165774668041.4038210342165855.70122819668149.786521245
2165919.39972885668307.369758387
#Sta/Elev= 30
       0 1633.75    11.8  1631.3    36.1  1627.8      75 1622.53    93.7 1620.86
   116.4 1620.45   124.9 1620.72   136.2  1621.7   168.3 1622.64   204.5 1621.34
   219.9 1620.05   224.4    1620   228.9 1618.93   233.1 1617.77   237.4 1617.84
   240.51619.078   241.7 1619.69   250.3 1627.02   264.1 1635.22   272.1    1638
   276.2 1638.33   283.3 1637.78   289.1 1638.05   293.5 1639.88   297.8 1642.86
   302.8 1645.76   306.4 1647.12   314.8 1649.29   321.3 1651.44   334.6 1656.51
#Mann= 5 ,-1,0
       0      .1       0   228.9    .045       0   240.5      .1       0
  244.67     .06       0  294.67      .1       0
Bank Sta=228.9,240.5
XS Rating Curve= 0 ,0
Exp/Cntr(USF)=0,0
Exp/Cntr=0.3,0.1

Type RM Length L Ch R = 1 ,1840    ,280.6,278.2,267.2
XS GIS Cut Line= 3
2165570.04336316668149.2331608292165601.36324348668239.302799242
2165601.79301322668379.157042657
#Sta/Elev= 30
       0  1630.2    17.3 1627.43    25.4 1625.54    33.8 1622.94    42.3 1618.88
    46.5 1617.87    67.7 1617.16    76.2 1617.37    80.4 1617.72    88.9 1619.76
    93.1 1620.22    97.2  1620.3   101.2 1620.11   117.2 1617.93   133.2 1617.46
   141.2 1617.79   145.51616.546   149.2 1615.54   153.2 1615.69   157.2 1616.62
   161.2  1617.9   169.2 1618.83   181.2 1624.38   185.2 1625.98   189.2  1627.1
   197.2  1628.7   209.2 1630.41   217.2 1631.91   225.2 1633.62   235.2 1636.46
#Mann= 5 ,-1,0
       0      .1       0  125.36     .06       0   145.5    .045       0
   157.2     .06       0  225.36      .1       0
Bank Sta=145.5,157.2
XS Rating Curve= 0 ,0
Exp/Cntr(USF)=0,0
Exp/Cntr=0.3,0.1

Type RM Length L Ch R = 1 ,1562    ,173.3,171.9,169.6
XS GIS Cut Line= 5
2165326.88107274668176.8797593572165350.09762343668211.124171628
2165409.88024146668310.3749258372165452.83086024668372.479198939
2165487.65568628668412.527748883
#Sta/Elev= 30
       0 1654.32     9.8 1649.13    24.2 1642.93    34.2 1638.17    43.8 1633.19
    48.4 1630.07    53.1 1626.48      59 1620.44    62.4 1617.34    67.61614.947
    71.8 1613.91    76.4 1613.69    81.61614.736    85.8 1615.43    93.9 1615.17
    99.8 1614.69   107.4 1614.85   108.5 1615.08   114.3 1617.36   117.2 1617.75
   131.8 1617.87   137.2 1618.16   143.5 1619.04   155.8 1621.62   165.5 1622.84
   198.3 1624.41   206.6 1625.02   243.9 1629.69   258.3 1630.97   285.8 1634.88
#Mann= 3 ,-1,0
       0      .1       0    67.6    .045       0    81.6      .1       0
Bank Sta=67.6,81.6
XS Rating Curve= 0 ,0
Exp/Cntr(USF)=0,0
Exp/Cntr=0.3,0.1

Type RM Length L Ch R = 1 ,1390    ,183.8,184.6,181.8
XS GIS Cut Line= 4
2165193.95060288668273.695152483 2165206.8486866668313.034307822
2165294.55565588668413.6393608222165322.93144006668467.166408251
#Sta/Elev= 30
       0 1632.53    12.1 1628.65    20.5  1626.3    33.1 1621.98    37.3 1620.74
    43.4 1619.28    52.2 1617.87    62.8 1615.79      68 1615.04      85 1614.69
    92.1 1614.81    96.3 1614.34    98.2 1613.77     102 1612.96   104.3 1612.76
   107.6 1613.33   109.1 1613.79   113.3 1614.87   116.5 1615.23   121.8 1614.88
   142.4 1614.41   146.9 1615.15     153 1617.13   158.3 1618.56     169 1620.48
   174.9  1621.1   196.4 1624.21     206 1625.29   215.1  1625.6   235.5 1627.18
#Mann= 4 ,-1,0
       0      .1       0    98.2    .045       0   109.1      .1       0
  234.87     .06       0
Bank Sta=98.2,109.1
XS Rating Curve= 0 ,0
Exp/Cntr(USF)=0,0
Exp/Cntr=0.3,0.1

Type RM Length L Ch R = 1 ,1206    ,298.2,309.2,306.8
XS GIS Cut Line= 3
 2165067.9659175668375.143364558 2165084.2318922668418.204336299
2165220.09113612668561.347581092
#Sta/Elev= 30
       0 1629.87     2.2 1629.62      10 1627.38      15 1626.24    23.6 1624.86
    32.1 1623.01    51.8 1619.63    65.1 1614.91    69.2 1613.72      75 1613.34
    86.6 1613.48    96.2 1613.92   110.8 1613.65   116.3 1614.04   121.5 1614.04
   127.3 1612.53   130.1 1612.01     133 1611.79  135.41 1612.53   138.6 1613.84
   149.4 1617.35   155.6 1617.91   158.4 1618.44   186.7 1625.76   193.5 1626.36
   208.6 1626.46   226.6  1627.2   231.9    1628   237.7  1629.5   243.4  1632.1
#Mann= 3 ,-1,0
       0      .1       0   127.3    .045       0  135.41      .1       0
Bank Sta=127.3,135.41
XS Rating Curve= 0 ,0
Exp/Cntr(USF)=0,0
Exp/Cntr=0.3,0.1

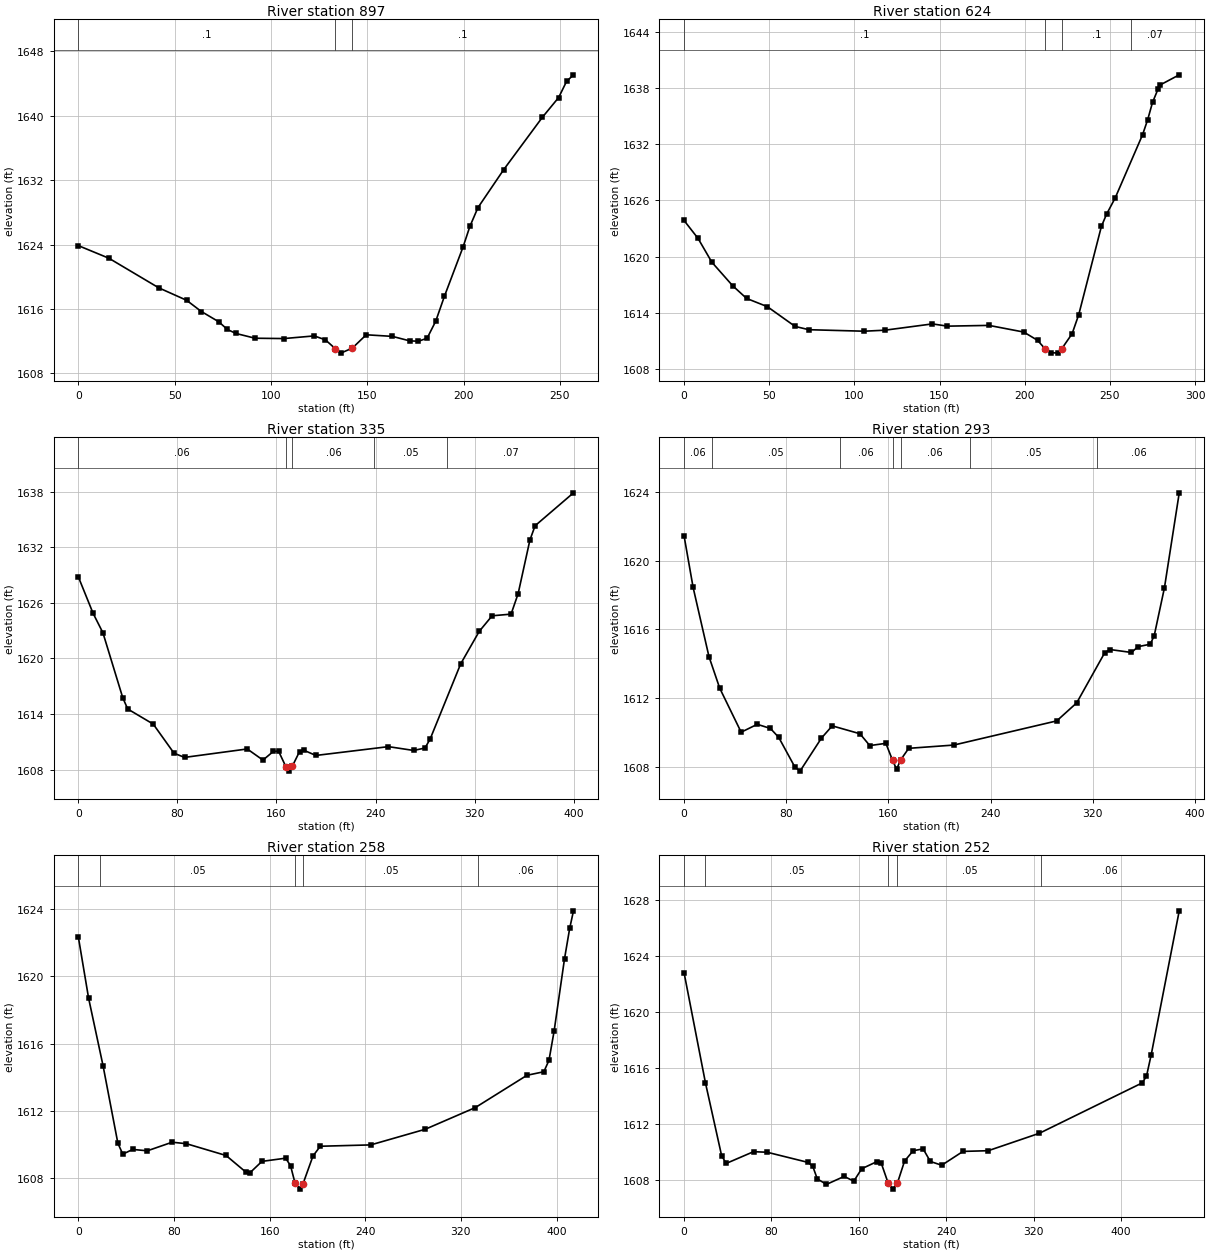
Type RM Length L Ch R = 1 ,897     ,264.3,272.2,270.2
XS GIS Cut Line= 4
2164885.43383121668470.4658507332164905.42586097668519.478568861
2164973.14080049668649.7492144112164989.90830932668704.566070212
#Sta/Elev= 30
       0 1623.87    15.9  1622.3    41.8 1618.62    56.2 1617.08    63.9 1615.68
    72.9 1614.41    77.4 1613.45    81.9 1612.95    91.8 1612.36   106.8 1612.32
   122.5 1612.65   128.3 1612.16   133.4 1611.07   136.3 1610.51   142.3 1611.14
   149.5 1612.79   163.1 1612.59   172.1 1612.03   176.6 1611.99   181.1 1612.36
   185.6 1614.49   190.1 1617.58   199.8 1623.72   203.3 1626.25   207.5 1628.59
   220.9 1633.32     241 1639.83   249.4 1642.27   253.5 1644.27   257.1 1645.09
#Mann= 3 ,-1,0
       0      .1       0   133.4    .045       0   142.3      .1       0
Bank Sta=133.4,142.3
XS Rating Curve= 0 ,0
Exp/Cntr(USF)=0,0
Exp/Cntr=0.3,0.1

Type RM Length L Ch R = 1 ,624     ,286.2,289,288.7
XS GIS Cut Line= 3
2164754.45377117668505.1056592732164798.37133872668743.442141483
2164818.48976238668787.459642869
#Sta/Elev= 30
       0 1623.86     8.2 1621.95    16.3 1619.41    28.5  1616.9    36.7 1615.54
    48.9 1614.66    65.2 1612.55    73.3  1612.2   105.8 1612.04     118 1612.15
   145.8 1612.82   154.6 1612.58     179 1612.66   199.4 1611.95   207.5 1611.07
   211.91610.166   215.6 1609.75   219.7  1609.7   221.81610.187   227.8 1611.77
   231.7 1613.81     245 1623.23     248 1624.52   253.1 1626.27   269.2 1633.03
   272.2 1634.64     275 1636.46   278.2 1637.87   279.4 1638.32   290.7 1639.41
#Mann= 4 ,-1,0
       0      .1       0   211.9    .045       0   221.8      .1       0
  262.35     .07       0
Bank Sta=211.9,221.8
XS Rating Curve= 0 ,0
Exp/Cntr(USF)=0,0
Exp/Cntr=0.3,0.1

Type RM Length L Ch R = 1 ,335     ,42.5,42.6,42.8
XS GIS Cut Line= 5
2164523.49480173668533.3323911422164522.20499336 668582.34510927
2164598.30368729 668808.706478522164658.27977658668885.450076641
2164668.59824356668895.768543616
#Sta/Elev= 30
       0 1628.81    11.9 1624.88    19.9 1622.76    35.9 1615.76    39.9 1614.55
    60.5 1612.92    77.3 1609.78    85.8 1609.33   136.4 1610.24   149.1 1609.04
   157.5 1609.98   161.7    1610   167.61608.323   170.2 1607.85   172.8 1608.38
   178.6 1609.95   182.3 1610.09   191.8 1609.54   250.4 1610.49   270.7 1610.08
   279.9 1610.34   284.1 1611.32   308.7 1619.41   323.7 1622.92   334.1  1624.6
   349.4 1624.78   355.1 1626.98   364.6 1632.76   368.8 1634.31   399.8 1637.86
#Mann= 5 ,-1,0
       0     .06       0   167.6    .045       0   172.8     .06       0
  239.03     .05       0  297.84     .07       0
Bank Sta=167.6,172.8
XS Rating Curve= 0 ,0
Exp/Cntr(USF)=0,0
Exp/Cntr=0.3,0.1

Type RM Length L Ch R = 1 ,293     ,34.3,34.8,35.6
XS GIS Cut Line= 5
    2164474.5379668550.0599859532164473.55827764668561.833853346
2164525.37476412668725.688701029 2164578.0454025668899.247723041
2164598.89143356668908.198671056
#Sta/Elev= 30
       0 1621.46     7.1 1618.45    19.5 1614.42    27.9 1612.58    44.7 1610.01
    57.3 1610.47    67.6 1610.23    74.1 1609.71    86.6    1608    90.8 1607.74
   107.6 1609.67     116 1610.38   137.7 1609.92   145.4 1609.23     158 1609.36
   163.2 1608.38   166.4 1607.85   169.6  1608.4   175.9 1609.07   211.2 1609.26
   291.8 1610.67   307.4 1611.72   329.4 1614.65   333.6 1614.83   350.3 1614.66
   355.5    1615     365 1615.14   368.1 1615.64   376.1 1618.43   387.7 1623.97
#Mann= 7 ,-1,0
       0     .06       0   21.81     .05       0  121.81     .06       0
   163.2    .045       0   169.6     .06       0  223.67     .05       0
  323.67     .06       0
Bank Sta=163.2,169.6
XS Rating Curve= 0 ,0
Exp/Cntr(USF)=0,0
Exp/Cntr=0.3,0.1

Type RM Length L Ch R = 1 ,258     ,6.8,5.6,4.6
XS GIS Cut Line= 5
2164451.08964148668548.5845199212164450.08439799668566.721882496
2164493.39596489668737.8412755862164562.81470494 668908.87950221
2164595.13269341668922.050581865
#Sta/Elev= 30
       0 1622.36     8.6 1618.71    20.7 1614.69    33.1 1610.08    37.2 1609.43
    45.5 1609.71    57.8 1609.63    78.5 1610.14    90.5 1610.05   123.6 1609.35
   140.2 1608.36   143.7 1608.33   153.6    1609   173.4 1609.19   177.5 1608.75
   181.31607.706   185.7 1607.35     1881607.675   196.3 1609.32   202.4  1609.9
   244.6 1609.98   290.2 1610.91   332.1  1612.2   375.3 1614.12   389.4 1614.33
   393.7 1615.01     398 1616.75   406.7 1621.05     411 1622.85   414.2  1623.9
#Mann= 5 ,-1,0
       0     .06       0   18.17     .05       0   181.3    .045       0
     188     .05       0  334.68     .06       0
Bank Sta=181.3,188
XS Rating Curve= 0 ,0
Exp/Cntr(USF)=0,0
Exp/Cntr=0.3,0.1

Type RM Length L Ch R = 1 ,252     ,250.7,252.4,250.7
XS GIS Cut Line= 6
2164437.11838971668547.4050189682164436.40105979668566.977408291
2164482.81657835668723.0011993412164490.43276781668742.041672978
2164562.36344599668940.0625987992164601.99809643668943.882430781
#Sta/Elev= 30
       0 1622.83    19.6 1614.94    34.4 1609.73    38.6 1609.18    63.6 1610.02
    76.1 1609.98   113.7 1609.25   117.9 1608.96     122 1608.07   130.4 1607.68
   146.6 1608.25   155.4 1607.91   162.7  1608.8   176.3  1609.3   180.5 1609.21
   186.91607.766   191.2 1607.34   195.41607.786   201.9 1609.35   209.8 1610.09
   218.9 1610.22   225.5 1609.32   235.9 1609.05   255.4 1610.04   278.5 1610.09
   325.4 1611.34   419.4 1614.94   423.4 1615.42   427.7 1616.95   453.4 1627.26
#Mann= 5 ,-1,0
       0     .06       0   19.59     .05       0   186.9    .045       0
   195.4     .05       0     327     .06       0
Bank Sta=186.9,195.4
XS Rating Curve= 0 ,0
Exp/Cntr(USF)=0,0
Exp/Cntr=0.3,0.1

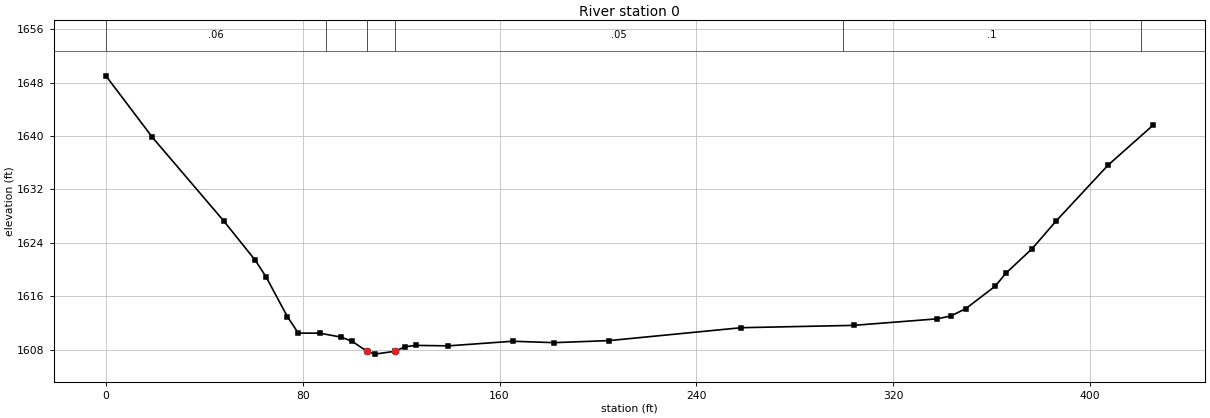
Type RM Length L Ch R = 1 ,0       ,19.4,18.4,17.8
XS GIS Cut Line= 4
2164376.52346549668482.8947866162164364.34194191 668530.90432072
2164236.74730892 668825.762055262164199.89409635668866.264395063
#Sta/Elev= 30
       0 1649.03    18.9 1639.81    47.8 1627.32    60.7 1621.39    65.1  1618.9
    73.8 1612.91    78.2 1610.47    86.9 1610.46    95.6 1609.87     100 1609.25
   106.1 1607.75   109.2 1607.32   117.4 1607.74   121.7 1608.44   126.1 1608.63
   139.2 1608.56   165.3 1609.25   182.2 1609.04   204.6 1609.35   258.2 1611.28
   303.9 1611.63   337.9 1612.61   343.4 1613.04   349.5 1614.14   361.5 1617.52
   365.8 1619.45   376.5 1623.14   386.2 1627.27   407.3 1635.64   425.6 1641.63
#Mann= 6 ,-1,0
       0     .06       0   89.53     .05       0   106.1    .045       0
   117.4     .05       0  299.53      .1       0  420.81     .05       0
Bank Sta=106.1,117.4
XS Rating Curve= 0 ,0
Exp/Cntr=0.3,0.1
LCMann Table=0

Chan Stop Cuts=-1
Use User Specified Reach Order=0
Composite Channel Slope=5